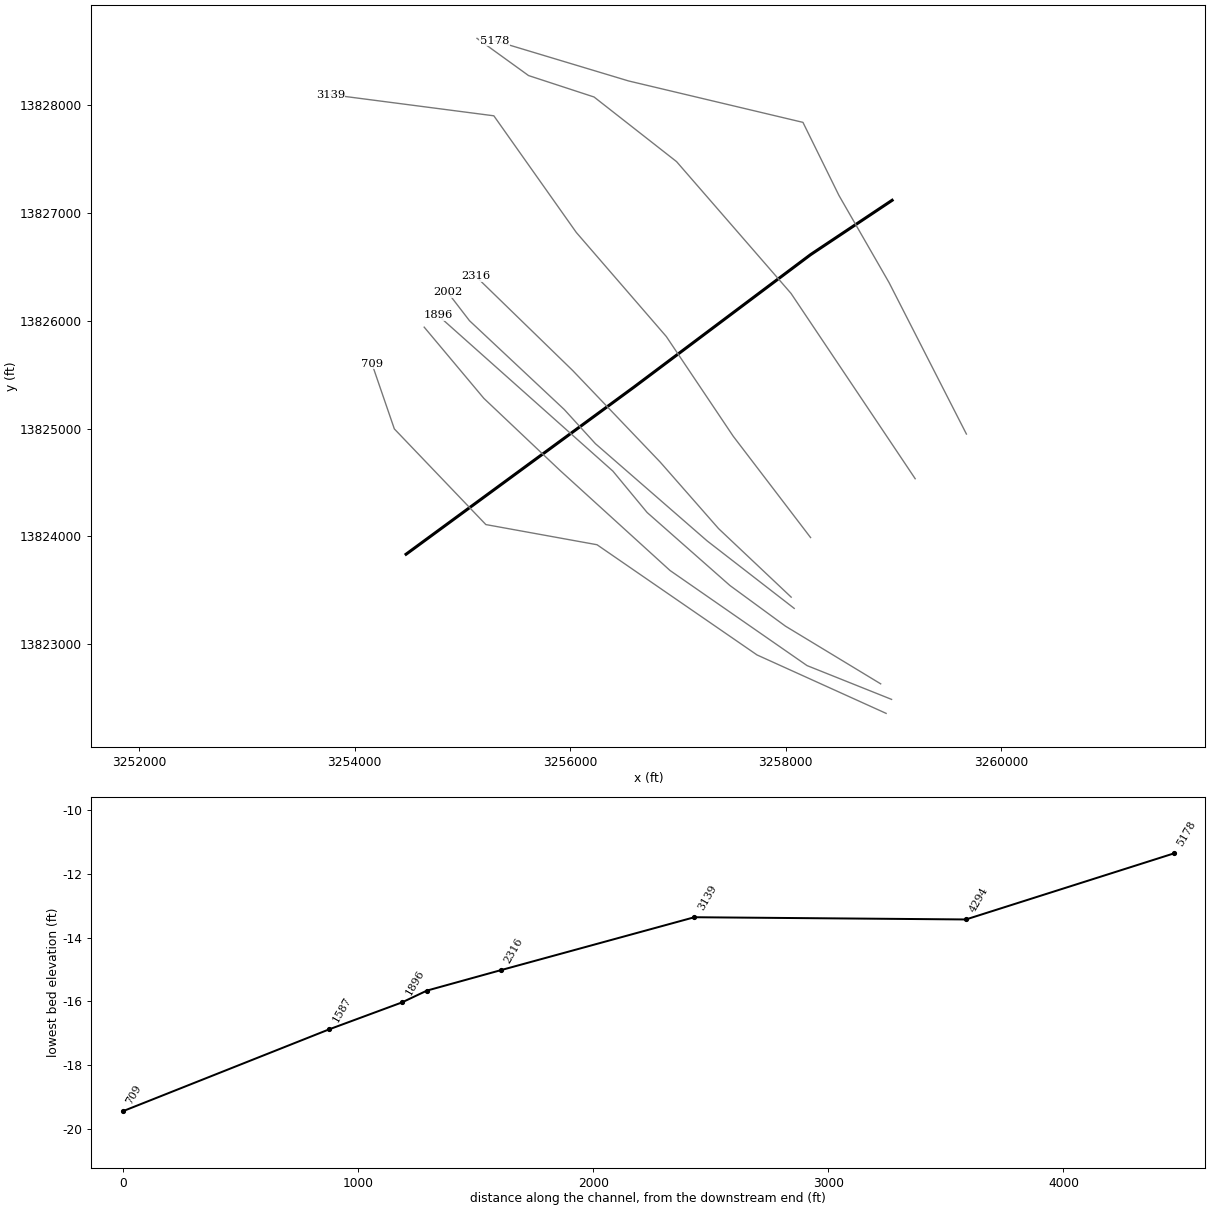
--- Q200-00-00.prj (project) ---

Proj Title=Q200-00-00
Current Plan=p04
Default Exp/Contr=.3,.1
English Units
Geom File=g04
Flow File=f01
Flow File=f04
Plan File=p03
Plan File=p04
Y Axis Title=Elevation
X Axis Title(PF)=Main Channel Distance
X Axis Title(XS)=Station
BEGIN DESCRIPTION:
Cedar Bayou Watershed
Cedar Bayou Diversion Channel
HCFCD Unit Q 200-00-00
(Flood Hazard) Model
10, 2, 1, 0.2% Event
Filename q2000000.prj
Prepared by:  FTN Associates Ltd.   DATE:  May 2003
Reviewed by:     DATE:
STATUS (FINAL RAS)
Starting water surface elevation based upon mean high tide (MHT) at Morgans Point of 1.5' for all profiles
Manning's "n" values were adjusted as appropriate based on field recon notes and observations.
END DESCRIPTION:
DSS Export Rating Curves= 0
DSS Export Rating Curve Sorted= 0
DSS Export Volume Flow Curves= 0
DXF OffsetX= 0
DXF OffsetY= 0
DXF ScaleX= 1
DXF ScaleY= 10

--- Q200-00-00.p04 (plan) ---

Plan Title=Floodway
Version=Version 3.0.1  Mar 2001
Short Identifier=Floodway0607
Geom File=g04
Flow File=f04
Subcritical Flow
K Sum by GR= 0
Std Step Tol= 0.01
Critical Tol= 0.01
Num of Std Step Trials= 20
Max Error Tol= 0.3
Flow Tol Ratio= 0.001
Split Flow NTrial= 30
Split Flow Tol= 0.02
Split Flow Ratio= 0.02
Log Output Level= 0
Friction Slope Method= 1
Unsteady Friction Slope Method= 2
Parabolic Critical Depth
Global Vel Dist= 0 , 0 , 0
Global Log Level= 0
CheckData=True
Encroach Param=-1 ,0,0, 2
Encroach River=Q200-00-00
Encroach Reach=CB Diversion
Encroach Node=5178
       1    1967    2486
Encroach Node=4294
       1    2046 2491.47
Encroach Node=3139
       1    1904    2334
Encroach Node=2316
       1    2281    2627
Encroach Node=2002
       1    3541    3886
Encroach Node=1951
       1    3540    3886
Encroach Node=1896
       1    3540    3885
Encroach Node=1587
       1    3825    4171
Encroach Node=709
       1    4225    4536
Encroach Reach=Q200-00-00_0007
Encroach Node=5178
       1    1967    2486
Encroach Node=4294
       1    2046 2491.47
Encroach Node=3139
       1    1904    2334
Encroach Node=2316
       1    2281    2627
Encroach Node=2002
       1    3541    3886
Encroach Node=1951
       1    3540    3886
Encroach Node=1896
       1    3540    3885
Encroach Node=1587
       1    3825    4171
Encroach Node=709
       1    4225    4536
Computation Interval=1HOUR
Output Interval=1HOUR
Run HTab= 0
Run UNet= 0
Run PostProcess= 0
UNET Theta= 1
UNET ZTol= 0.02
UNET ZSATol= 0.1
UNET MxIter= 20
UNET MaxInSteps= 20
UNET DtIC= 0
UNET DtMin= 0
UNET MaxCRTS= 20
UNET WFStab= 2
UNET SFStab= 1
UNET WFX= 1
UNET SFX= 1
UNET Convert EG Bridges=-1
UNET Use Existing IB Tables=-1
Instantaneous Interval=1HOUR
Write IC File= 0
Write Velocity= 0
Write Detailed= 0

--- Q200-00-00.p03 (plan) ---

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Plan Title=FEMA Effective June 2007
Short Identifier=FEMAeff0607
Geom File=g04
Flow File=f01
Encroach Param=-1 ,0,0, 0

--- Q200-00-00.f04 (steady flow) ---

Flow Title=Floodway
Version=Version 3.0.1  Mar 2001
Number of Profiles= 2
Profile Names=1PCT_100yr,1PCTFloodway_100yrFW
River Rch & RM=Q200-00-00,Q200-00-00_0007 ,5178
   13346   13346
Boundary for River Rch & Prof#=Q200-00-00,Q200-00-00_0007 , 1
Up Type= 0
Dn Type= 1
Dn Known WS=1.5
Boundary for River Rch & Prof#=Q200-00-00,Q200-00-00_0007 , 2
Up Type= 0
Dn Type= 1
Dn Known WS=1.5
DSS Import GetInterval= 0
DSS Import GetPeak= 0
DSS Import FillOption= 0

--- Q200-00-00.f01 (steady flow) ---

Flow Title=FEMA Effective June 2007
Version=Version 3.0.1  Mar 2001
Number of Profiles= 4
Profile Names=10PCT_10yr,2PCT_50yr,1PCT_100yr,0.2PCT_500yr
River Rch & RM=Q200-00-00,Q200-00-00_0007 ,5178
    8923   11752   13346   18637
Boundary for River Rch & Prof#=Q200-00-00,Q200-00-00_0007 , 1
Up Type= 0
Dn Type= 1
Dn Known WS=1.5
Boundary for River Rch & Prof#=Q200-00-00,Q200-00-00_0007 , 2
Up Type= 0
Dn Type= 1
Dn Known WS=1.5
Boundary for River Rch & Prof#=Q200-00-00,Q200-00-00_0007 , 3
Up Type= 0
Dn Type= 1
Dn Known WS=1.5
Boundary for River Rch & Prof#=Q200-00-00,Q200-00-00_0007 , 4
Up Type= 0
Dn Type= 1
Dn Known WS=1.5
DSS Import GetInterval= 0
DSS Import GetPeak= 0
DSS Import FillOption= 0

--- Q200-00-00.g04 (geometry) ---

Geom Title=Q200-00-00 June 2007
Version=Version 3.0.1  Mar 2001

River Reach=Q200-00-00      ,Q200-00-00_0007
Reach XY= 30
     3258987.938    13827118.897     3258662.679    13826902.067
      3258625.81     13826877.49     3258555.593     13826830.68
     3258408.846    13826732.854     3258261.542    13826634.655
     3258231.616    13826614.706     3257860.225    13826336.162
     3257810.585    13826298.933     3257759.104    13826260.321
     3257710.601    13826223.945     3257472.781     13826045.58
     3257421.349    13826007.005     3256926.392    13825635.788
     3256922.992    13825633.237     3256842.213    13825572.654
     3256752.301    13825505.219     3256698.293    13825464.714
     3256594.175    13825386.625     3256068.899    13825001.423
     3255667.926    13824707.375     3255549.703    13824620.679
      3255546.67    13824618.454     3255457.676    13824553.192
     3255406.815    13824515.895     3255368.753    13824487.982
     3255187.684    13824355.199     3255060.123    13824261.653
     3255032.076    13824241.086     3254476.794    13823833.879

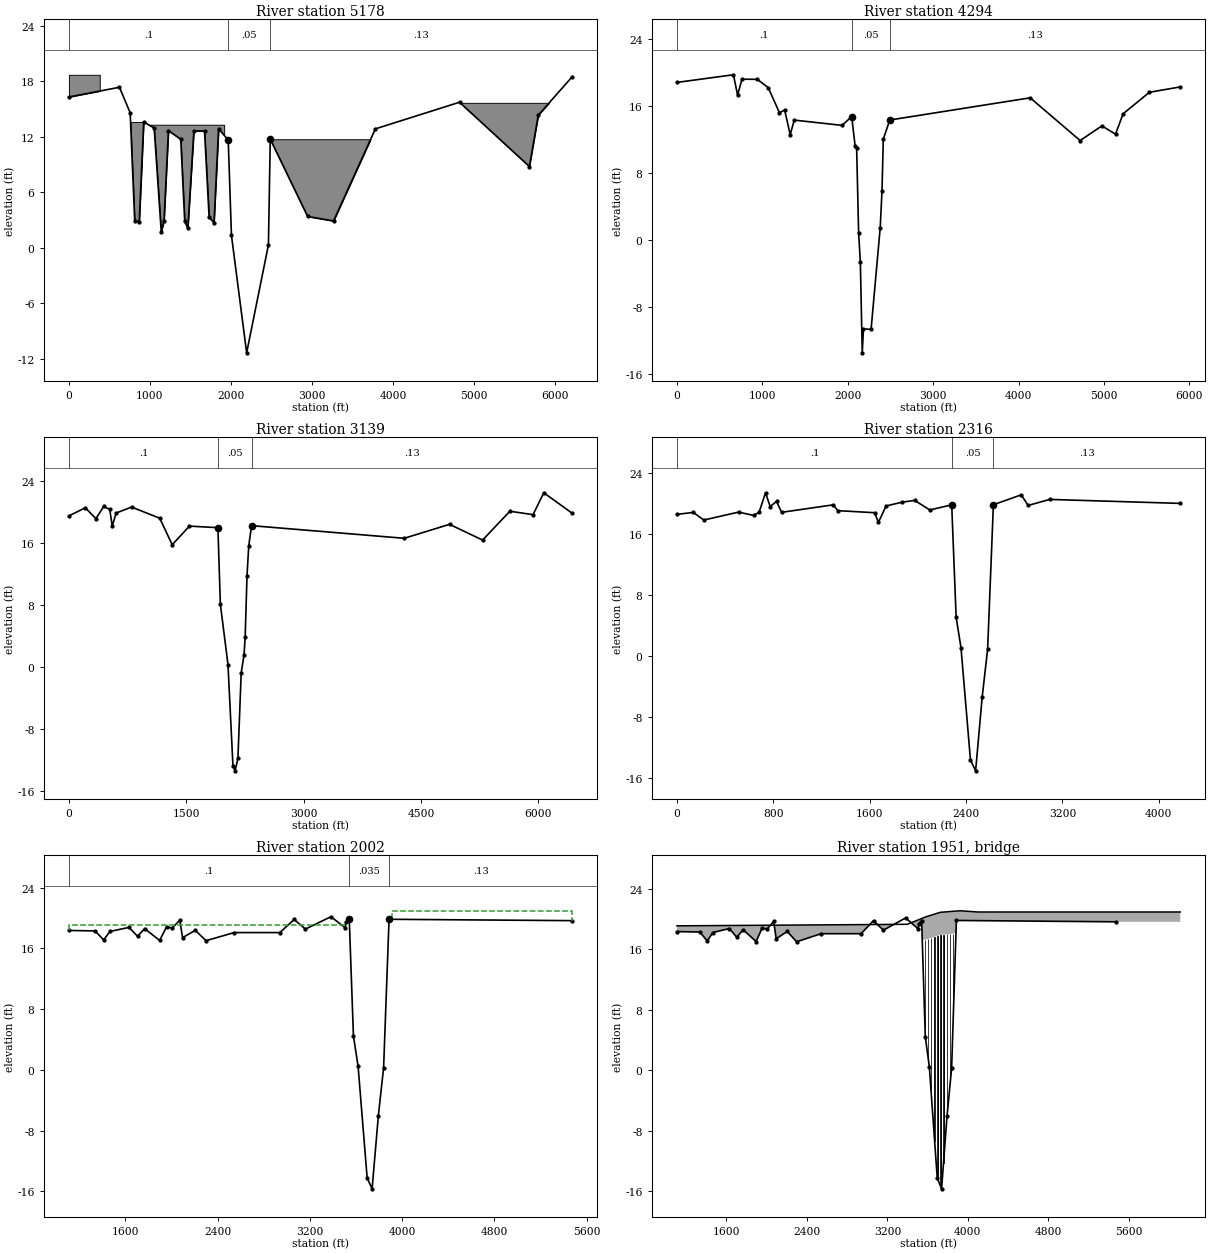
Type RM Length L Ch R = 1 ,5178    ,847.03,884.32,946.66
BEGIN DESCRIPTION:
Valley section 431v1
Bank Station offset =      2806
Set Multiple Blocked Obstructions to contain 100 and 500-year flows.  The blocked areas do not convey water in the stream and are blocked to exclude these areas from storage..
Adjusted Manning's "n" values to correspond to values which represent high weeds.
END DESCRIPTION:
XS GIS Cut Line= 6
     3259677.306    13824949.487     3258959.232    13826355.294
     3258494.001    13827164.391     3258160.249     13827842.01
     3256542.054    13828226.331 3255297.905712113828600.6641271
#Sta/Elev= 30
       0   16.31   624.2   17.36  756.58    14.6  812.33    2.94  868.53    2.81
  923.81    13.6 1052.73   12.96 1140.11    1.72 1174.45    2.92  1228.9   12.67
 1380.91   11.74 1429.93    2.87  1468.3    2.09 1543.14   12.65 1674.17   12.64
    1731    3.34 1791.33    2.69 1848.22   12.87    1967   11.66  2006.8    1.35
 2194.36  -11.36 2463.26     .31    2486   11.74 2947.19    3.39 3267.33     2.9
 3783.46   12.86  4822.3   15.74 5684.88    8.79 5794.86   14.34 6213.73    18.5
#Mann= 3 ,-1 , 0
       0      .1       0    1967     .05       0    2486     .13       0
#Block Obstruct= 5 ,-1
       0  380.84   18.71  740.67  923.81    13.6     940 1916.95   13.31
    2486    3783   11.74  4838.1    6000   15.68
Bank Sta=1967,2486
XS Rating Curve= 0
Exp/Cntr=.3,.1

Type RM Length L Ch R = 1 ,4294    ,1176.92,1154.68,1133.97
BEGIN DESCRIPTION:
Valley section 431v2
Bank Station offset =      2830
Adjusted Manning's "n" values to correspond to values which represent high weeds.
Moved channel bank stations to 2046 and 2491.47
END DESCRIPTION:
XS GIS Cut Line= 6
     3259201.961    13824534.825     3258049.578    13826254.626
     3256987.058    13827477.916     3256221.545    13828077.414
      3255613.82     13828276.21     3255135.167    13828621.852
#Sta/Elev= 30
       0   18.85  661.41   19.76  710.18   17.34  761.39   19.23   940.7   19.22
 1069.28   18.22  1200.7   15.22 1261.03   15.56 1326.05   12.61 1373.71   14.35
 1934.12   13.72    2046   14.78 2085.77   11.29    2104   11.03 2127.27     .87
 2147.38   -2.58 2169.62  -13.43 2183.75  -10.57 2273.04  -10.63 2379.91     1.5
 2400.89     5.9    2416   12.07 2491.47   14.36 4135.86   17.01 4720.57   11.91
 4975.26   13.66 5135.06   12.67  5223.3    15.1 5530.88   17.67 5892.76   18.31
#Mann= 3 , 0 , 0
       0      .1       0    2046     .05       0 2491.47     .13       0
Bank Sta=2046,2491.47
XS Rating Curve= 0
Exp/Cntr=.3,.1

Type RM Length L Ch R = 1 ,3139    ,796.52,823.56,849.01
BEGIN DESCRIPTION:
Valley section 431v3
Bank Station offset =      2876
Adjusted Manning's "n" values to correspond to values which represent high weeds.
Moved right channel bank station to 2334
END DESCRIPTION:
XS GIS Cut Line= 6
     3258231.045    13823988.685     3257512.971     13824929.26
     3256892.138    13825854.511     3256056.596    13826820.525
     3255291.476     13827902.89     3253773.727    13828100.178
#Sta/Elev= 30
       0   19.52  209.81   20.57  344.92   19.16  445.41   20.74  521.91   20.35
  554.07   18.22  604.62   19.89  800.61   20.66 1160.39   19.22 1320.15    15.8
 1540.45    18.2    1904      18  1935.2    8.14 2032.71     .35 2096.29  -12.71
 2123.66  -13.36 2159.67  -11.75 2201.66    -.73 2237.23    1.55 2252.35    3.91
    2276   11.82 2297.96   15.64    2334   18.26 4284.71   16.63 4863.34   18.43
 5286.01    16.4 5634.94   20.12 5930.63   19.68 6068.11    22.5  6431.2   19.86
#Mann= 3 , 0 , 0
       0      .1       0    1904     .05       0    2334     .13       0
Bank Sta=1904,2334
XS Rating Curve= 0
Exp/Cntr=.3,.1

Type RM Length L Ch R = 1 ,2316    ,318.39,313.97,310.5
BEGIN DESCRIPTION:
xsec 4/4 of 431s1u----- copy of section 431s1u
Bank Station offset =      2520
Set contraction/expansion coefficients.
Adjusted Manning's "n" values to correspond to values which represent high weeds.
Adjusted elevations based on the slope between RS 3139 and 2002.
END DESCRIPTION:
XS GIS Cut Line= 5
     3258051.029     13823435.68      3257377.39    13824071.544
     3256835.961    13824688.521     3256023.818    13825538.439
     3255123.535    13826413.539
#Sta/Elev= 30
       0   18.57  135.41   18.83  223.11   17.83  511.79   18.87   636.3   18.43
  682.19   18.85  735.51    21.4  774.13    19.6  826.86   20.27  869.09   18.84
 1297.63   19.82 1335.51   19.06 1640.71   18.79 1672.79   17.54 1736.22   19.67
 1872.06   20.18 1973.58    20.4 2099.52   19.15    2281   19.82 2317.76     5.1
  2358.1    1.11 2436.67   -13.6 2479.53  -15.02 2533.91   -5.37 2579.23     .91
    2627   19.83 2858.27   21.13 2915.45   19.74 3094.56   20.53 4178.27   20.01
#Mann= 3 , 0 , 0
       0      .1       0    2281     .05       0    2627     .13       0
Bank Sta=2281,2627
XS Rating Curve= 0
Exp/Cntr=.5,.3

Type RM Length L Ch R = 1 ,2002    ,84.39,106.01,120.91
BEGIN DESCRIPTION:
xsec 3/4 of 431s1----Survey section 431s1u
Bank Station offset =      2371
set contraction/expansion coefficients.
Applied Manning's "n" values that reflect the presence of a concrete lined channel.
Set normal ineffective flow stations based on Check-RAS.
END DESCRIPTION:
XS GIS Cut Line= 6
     3258079.339    13823331.293     3257270.242    13823958.343
     3256233.719     13824860.39     3255945.061    13825177.009
     3255065.452    13826001.314     3254863.178     13826264.27
#Sta/Elev= 30
    1110   18.36 1336.77    18.3 1411.61   17.11 1465.86   18.23 1631.03   18.76
 1704.96    17.6 1767.42    18.6 1896.63   17.04 1956.75   18.84 2004.52   18.66
 2071.06   19.71 2095.87   17.41 2206.06   18.38  2298.7   17.01 2542.91   18.08
 2939.83   18.08 3062.72   19.81 3160.85   18.54 3382.23   20.17 3507.74   18.69
 3509.93   19.41    3541   19.82  3577.2    4.46 3617.54     .47 3696.11  -14.24
 3738.97  -15.66 3793.35   -6.01 3838.67     .27    3886   19.83 5474.05   19.65
#Mann= 3 , 0 , 0
    1110      .1       0    3541    .035       0    3886     .13       0
#XS Ineff= 2 , 0
    1110 3518.52   19.12 3915.73    1110   20.95
Permanent Ineff=
       F       F
Bank Sta=3541,3886
XS Rating Curve= 0
Exp/Cntr=.5,.3

Type RM Length L Ch R = 3 ,1951    ,,,
BEGIN DESCRIPTION:
FM 2354    (431s1)
Did not use the reported survey d/s invert elevation as the channel had 12 to 15 ft of h2O at the time of survey and only one elevation was shot on d/s side of strxr.
END DESCRIPTION:
Bridge Culvert--1,0,-1,-1, 0
Deck Dist Width WeirC Skew NumUp NumDn MinLoCord MaxHiCord MaxSubmerge Is_Ogee
35.1,35.8,2.6,0, 12, 12, 19.32, , .95, 0, 0,0,,
    1110    3390 3398.38    3547    3547 3577.81 3726.77    3882    3882 3926.66
 4098.23    6110
   19.12   19.32   19.32   20.12   20.12   20.29   20.91   21.07   21.07   21.11
   20.95   20.95
     -20     -20     -20     -20   17.12   17.29   17.91   18.11     -20     -20
     -20     -20
       0     153 3397.38    3547    3547 3576.81 3725.77    3882    3882 3925.66
 4097.23    5400
   19.12   19.32   19.32   20.12   20.12   20.29   20.91   21.07   21.07   21.11
   20.95   20.95
     -20     -20     -20     -20   17.12   17.29   17.91   18.11     -20     -20
     -20     -20
Pier Skew, UpSta & Num, DnSta & Num=  ,3574.62, 4 ,3574.62, 4 , 3 , 3 , 0 ,,
     1.5     1.5       2       2
     -20   15.41   15.41   17.41
     1.5     1.5       2       2
     -20   15.41   15.41   17.41
Pier Skew, UpSta & Num, DnSta & Num=  ,3605.94, 4 ,3605.94, 4 , 3 , 3 , 0 ,,
     1.5     1.5       2       2
     -20   15.53   15.53   17.53
     1.5     1.5       2       2
     -20   15.53   15.53   17.53
Pier Skew, UpSta & Num, DnSta & Num=  ,3636.9, 4 ,3636.9, 4 , 3 , 3 , 0 ,,
     1.5     1.5       2       2
     -20   15.66   15.66   17.66
     1.5     1.5       2       2
     -20   15.66   15.66   17.66
Pier Skew, UpSta & Num, DnSta & Num=  ,3665.75, 4 ,3665.75, 4 , 3 , 3 , 0 ,,
     1.5     1.5       4       4
     -20   13.78   13.78   17.78
     1.5     1.5       4       4
     -20   13.78   13.78   17.78
Pier Skew, UpSta & Num, DnSta & Num=  ,3669.65, 4 ,3669.65, 4 , 3 , 3 , 0 ,,
     1.5     1.5       4       4
     -20   13.78   13.78    17.8
     1.5     1.5       4       4
     -20   13.78   13.78    17.8
Pier Skew, UpSta & Num, DnSta & Num=  ,3696.9, 4 ,3696.9, 4 , 3 , 3 , 0 ,,
     1.5     1.5       4       4
     -20   13.91   13.91   17.91
     1.5     1.5       4       4
     -20   13.91   13.91   17.91
Pier Skew, UpSta & Num, DnSta & Num=  ,3700.81, 4 ,3700.81, 4 , 3 , 3 , 0 ,,
     1.5     1.5       4       4
     -20   13.91   13.91   17.93
     1.5     1.5       4       4
     -20   13.91   13.91   17.93
Pier Skew, UpSta & Num, DnSta & Num=  ,3728.03, 4 ,3728.03, 4 , 3 , 3 , 0 ,,
     1.5     1.5       4       4
     -20   13.94   13.94   17.94
     1.5     1.5       4       4
     -20   13.94   13.94   17.94
Pier Skew, UpSta & Num, DnSta & Num=  ,3732.01, 4 ,3732.01, 4 , 3 , 3 , 0 ,,
     1.5     1.5       4       4
     -20   13.94   13.94   17.95
     1.5     1.5       4       4
     -20   13.94   13.94   17.95
Pier Skew, UpSta & Num, DnSta & Num=  ,3758.46, 4 ,3758.46, 4 , 3 , 3 , 0 ,,
     1.5     1.5       4       4
     -20   13.97   13.97   17.97
     1.5     1.5       4       4
     -20   13.97   13.97   17.97
Pier Skew, UpSta & Num, DnSta & Num=  ,3762.46, 4 ,3762.46, 4 , 3 , 3 , 0 ,,
     1.5     1.5       4       4
     -20   13.97   13.97   17.98
     1.5     1.5       4       4
     -20   13.97   13.97   17.98
Pier Skew, UpSta & Num, DnSta & Num=  ,3791.64, 4 ,3791.64, 4 , 3 , 3 , 0 ,,
     1.5     1.5       2       2
     -20   16.01   16.01   18.01
     1.5     1.5       2       2
     -20   16.01   16.01   18.01
Pier Skew, UpSta & Num, DnSta & Num=  ,3823.5, 4 ,3823.5, 4 , 3 , 3 , 0 ,,
     1.5     1.5       2       2
     -20   16.04   16.04   18.04
     1.5     1.5       2       2
     -20   16.04   16.04   18.04
Pier Skew, UpSta & Num, DnSta & Num=  ,3854.54, 4 ,3854.54, 4 , 3 , 3 , 0 ,,
     1.5     1.5       2       2
     -20   16.07   16.07   18.07
     1.5     1.5       2       2
     -20   16.07   16.07   18.07
BR Coef=-1 , 1 , 1 ,1.25, 0 ,,,.8,-1,2,0,
WSPro=,,,, 1 ,,,, 0 ,,,, 0 ,,,,-1 ,-1 ,-1 , 0 , 0 , 0 , 0 , 0
BC Design=,, 0 ,, 0 ,,,,,,

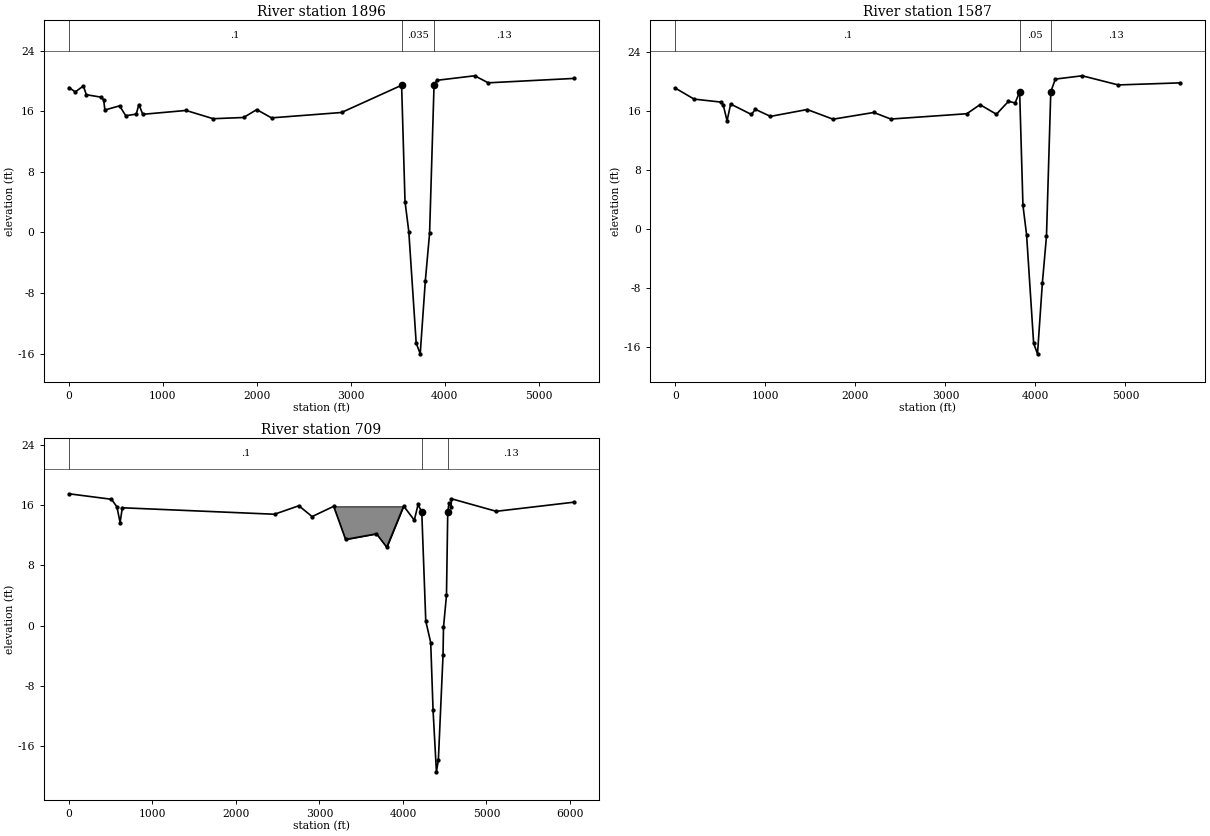
Type RM Length L Ch R = 1 ,1896    ,331.14,308.26,304.76
BEGIN DESCRIPTION:
xsec 2/4 of 431s1----copy of 431s1u.
Bank Station offset =      1262
Set contraction/expansion coefficients.
Applied Manning's "n" values that reflect the presence of a concrete lined channel.
Adjusted ground elevations based on the slope between RS 2002 and 709.  Did not use the reported survey d/s invert value as the channel had 12 to 15 ft of h2O at the time of survey and only one elevation was shot on d/s side of strxr.
Set normal ineffective flow stations based on CheckRAS. Check ie el's vs. wsel
END DESCRIPTION:
XS GIS Cut Line= 6
     3258881.717    13822631.023     3257997.787    13823166.512
      3257482.63    13823543.681     3256713.987      13824221.3
     3256396.593    13824605.068     3254772.154    13826051.882
#Sta/Elev= 30
       0   19.15      67   18.57  153.24   19.35  184.69    18.2  344.67   17.87
  369.28    17.5   382.4   16.18  538.62   16.73  603.92   15.43  715.58   15.63
  744.33    16.9  785.28   15.61 1245.92   16.12 1534.62   15.03 1858.77   15.19
 1998.34   16.23 2155.44   15.14  2900.5   15.85    3540   19.45 3576.17    4.09
 3616.51      .1 3695.08  -14.61 3737.94  -16.03 3792.32   -6.38 3837.64     -.1
    3885   19.46 3914.34    20.1 4317.93    20.7  4461.8   19.77 5371.39   20.35
#Mann= 3 , 0 , 0
       0      .1       0    3540    .035       0    3885     .13       0
#XS Ineff= 2 , 0
       0  3512.9    18.2 3915.94       0   19.53
Permanent Ineff=
       F       F
Bank Sta=3540,3885
XS Rating Curve= 0
Exp/Cntr=.5,.3

Type RM Length L Ch R = 1 ,1587    ,855.93,878.69,883.53
BEGIN DESCRIPTION:
xsec 1/4 of 431s1----copy of 431s1u.
Bank Station offset =       977
Adjusted Manning's "n" values to correspond to values which represent high weeds.
Adjusted ground elevations based on the slope between RS 2002 and 709.
END DESCRIPTION:
XS GIS Cut Line= 6
     3258982.693    13822486.772     3258198.342     13822800.39
     3256926.345    13823683.224       3255904.2    13824612.973
     3255199.083    13825280.316     3254645.063    13825941.363
#Sta/Elev= 30
       0   19.11  207.41   17.63  503.17   17.23  531.41   16.83  573.73   14.69
  613.57   16.96  844.72   15.55  887.29   16.25 1056.01   15.29 1463.85   16.22
  1750.9   14.91 2204.13   15.82 2393.08   14.93 3238.42   15.65  3384.5   16.88
 3566.95   15.58 3700.84   17.33 3774.82   17.11    3825   18.61 3861.64    3.25
 3901.98    -.74 3980.55  -15.45 4023.41  -16.87 4077.79   -7.22 4123.11    -.94
    4171   18.62 4221.41   20.34 4520.08   20.79 4920.87   19.55 5608.83   19.83
#Mann= 3 , 0 , 0
       0      .1       0    3825     .05       0    4171     .13       0
Bank Sta=3825,4171
XS Rating Curve= 0
Exp/Cntr=.3,.1

Type RM Length L Ch R = 1 ,709     ,569.37,708.68,945.52
BEGIN DESCRIPTION:
Valley section 431v4
Bank Station offset =       600
Adjusted Manning's "n" values to correspond to values which represent high weeds.
.
END DESCRIPTION:
XS GIS Cut Line= 6
     3258932.205    13822356.945     3257734.021    13822899.277
     3256249.123    13823922.076     3255217.341    13824109.236
     3254368.052     13824997.01     3254160.295    13825601.396
#Sta/Elev= 30
       0   17.52  508.89   16.79  574.15   15.79  612.35    13.7  638.95   15.66
 2461.46    14.8 2753.23   15.93 2911.54   14.49 3169.85   15.85 3312.39   11.45
 3682.32    12.2 3805.81   10.41 4007.82   15.89 4135.71   14.01 4180.83    16.1
    4225   15.07 4272.96      .6 4331.99   -2.26 4360.27  -11.27 4400.45  -19.44
 4423.69  -17.87 4479.46   -3.96 4485.01    -.24 4520.94    4.04    4536   15.06
  4550.4   16.24 4577.33   15.76 4579.08   16.86 5116.63   15.19 6044.56    16.4
#Mann= 3 , 0 , 0
       0      .1       0    4225     .05       0    4536     .13       0
#Block Obstruct= 1 ,-1
 3169.85 4007.82   15.85
Bank Sta=4225,4536
XS Rating Curve= 0
Exp/Cntr=.3,.1

Chan Stop Cuts=-1